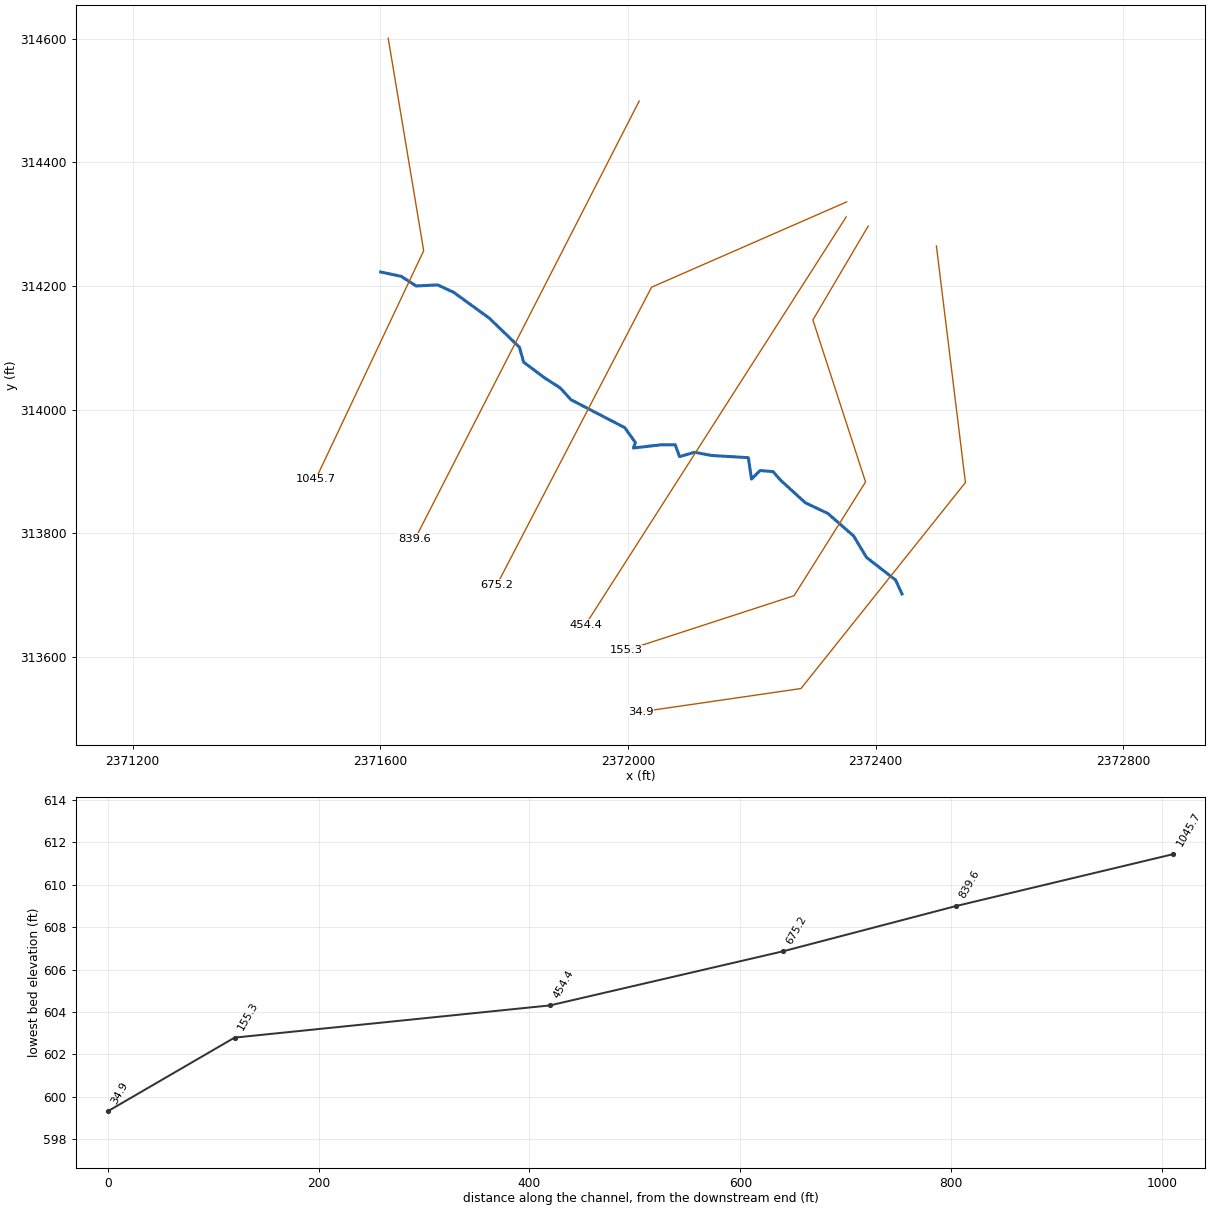
--- MILLTRIB2.prj (project) ---

Proj Title=MILLTRIB2
Current Plan=p01
Default Exp/Contr=0,0
English Units
Geom File=g01
Flow File=f01
Plan File=p01
BEGIN DESCRIPTION:
END DESCRIPTION:
DSS Export Rating Curves= 0
DSS Export Rating Curve Sorted= 0
DSS Export Volume Flow Curves= 0
DXF OffsetX= 0
DXF OffsetY= 0
DXF ScaleX= 0
DXF ScaleY= 0

--- MILLTRIB2.p01 (plan) ---

Plan Title=Floodplain
Program Version=4.00
Geom File=g01
Flow File=f01
K Sum by GR=0
Std Step Tol=0.01
Critical Tol=0.01
Num of Std Step Trials=20
Max Error Tol=0.3
Flow Tol Ratio=0.001
Split Flow NTrial=30
Split Flow Tol=0.02
Split Flow Ratio=0.02
Log Output Level=0
Friction Slope Method=1
Unsteady Friction Slope Method=2
Unsteady Bridges Friction Slope Method=1
Global Log Level=0
CheckData=False
Run HTab=0
Run UNet=0
Run PostProcess=0
UNET Theta=0
UNET Theta Warmup=0
UNET ZTol=0
UNET ZSATol=0
UNET MxIter=0
UNET MaxInSteps=0
UNET DtIC=0
UNET DtMin=0
UNET MaxCRTS=0
UNET WFStab=0
UNET SFStab=0
UNET WFX=0
UNET SFX=0
UNET DSS MLevel=0
UNET DZMax Abort=0
UNET Convert EG Bridges=0
UNET Use Existing IB Tables=0
UNET Froude Limit=0
UNET Froude Power=0
Write IC File=0
Echo Input=False
Echo Output=False
Write Detailed=0

--- MILLTRIB2.f01 (steady flow) ---

Flow Title=NFF Regression Equation
Program Version=4.10
Number of Profiles= 1
Profile Names=P100yr
River Rch & RM=MILLTRIB2,Main            ,1045.7
556.2527
River Rch & RM=MILLTRIB2,Main            ,454.4
561.1013
River Rch & RM=MILLTRIB2,Main            ,155.3
562.7159
Boundary for River Rch & Prof#=MILLTRIB2,Main            , 1
Up Type= 0
Dn Type= 3
Dn Slope=0.0271
DSS Import GetInterval= 0
DSS Import GetPeak= 0
DSS Import FillOption= 0

--- MILLTRIB2.g01 (geometry) ---

Geom Title=USGS 10m DEM
Program Version=4.10

River Reach=MILLTRIB2       ,Main
Reach XY= 30
     2371600.689      314222.679     2371633.676      314215.734
     2371657.981      314200.109     2371692.703      314201.845
     2371718.745      314189.692     2371776.036      314148.026
     2371824.648      314101.151     2371831.592      314076.845
     2371866.314      314050.804      2371890.62      314035.178
     2371907.981      314016.081     2371994.786      313970.942
     2372012.148      313946.637     2372008.675      313937.956
     2372053.814      313943.165     2372076.384      313943.165
     2372083.328      313924.067     2372107.634      313931.012
     2372135.411      313925.804     2372194.439      313922.331
     2372199.648      313887.609     2372213.537      313901.498
      2372234.37      313899.762     2372246.523      313885.873
     2372286.453      313849.415     2372322.911      313832.053
     2372364.578      313795.595     2372385.412      313760.873
     2372432.286      313724.415     2372442.703      313701.845

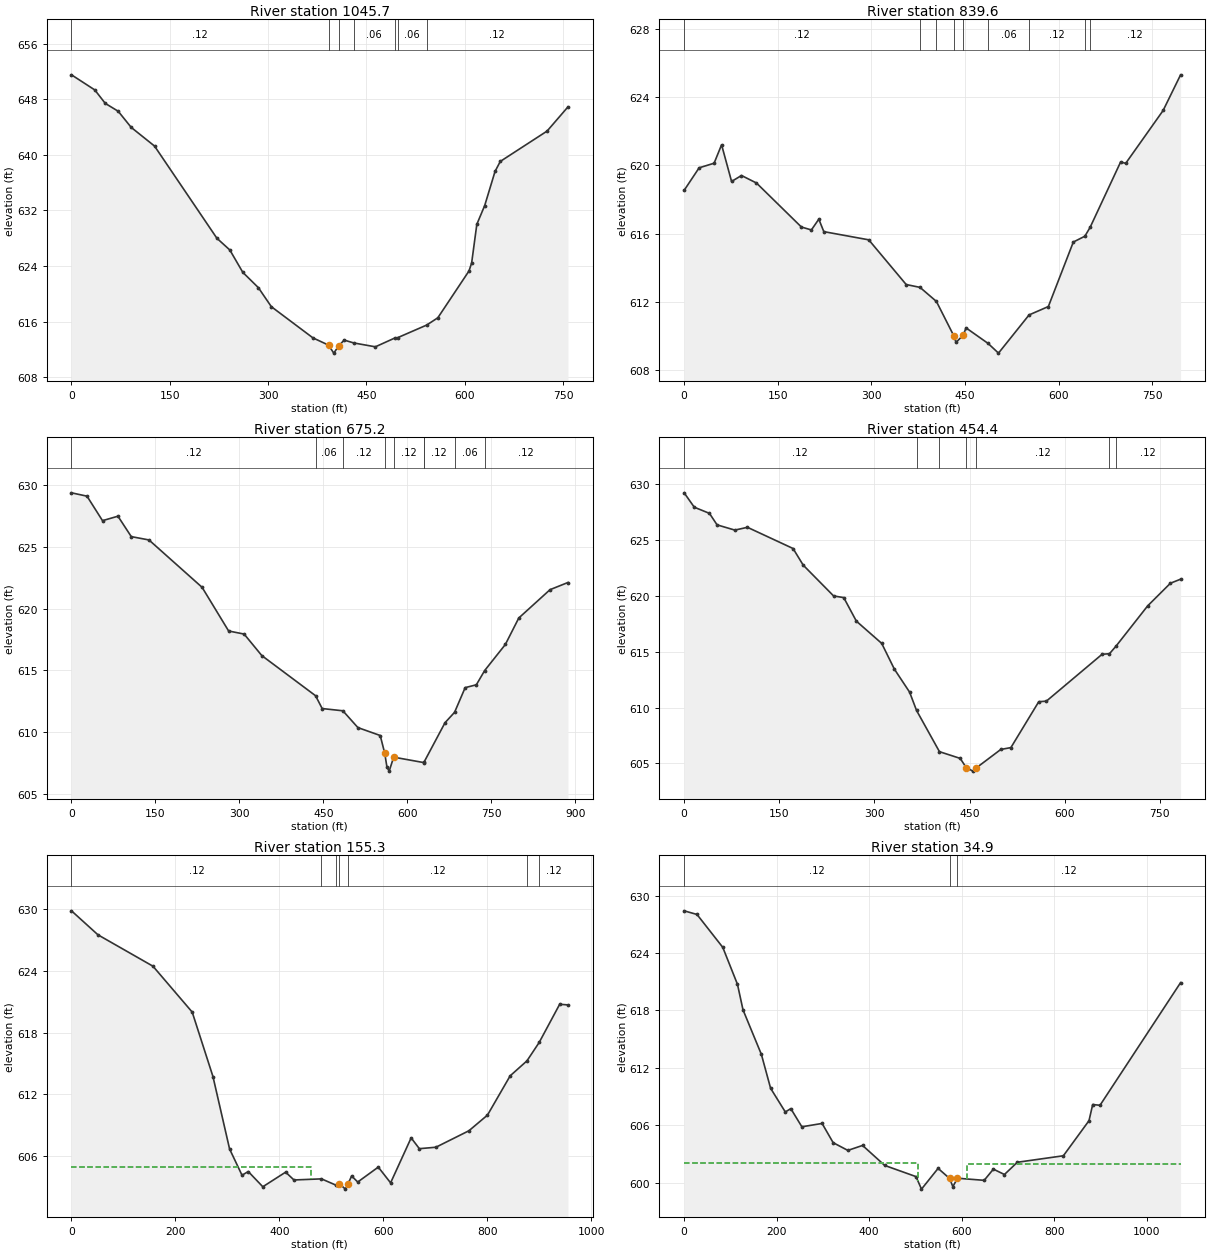
Type RM Length L Ch R = 1 ,1045.7  ,206.4,206.1,207.3
XS GIS Cut Line= 3
     2371612.825      314600.864     2371670.117      314257.114
     2371495.638      313887.322
#Sta/Elev= 30
       0  651.53    35.6  649.35    51.5  647.42    71.3  646.28    91.1  643.96
   126.7  641.27   221.8     628   241.6   626.3   261.4  623.08   285.1  620.88
   304.9  618.14   368.3  613.65   392.2   612.6   400.1  611.45     408  612.52
     416  613.33  430.58612.9172   463.6  612.36  493.28 613.627  497.89613.6864
  541.94615.4932   558.9  616.54   606.5  623.29   610.5  624.44   618.4     630
   630.4   632.7   646.2  637.62   654.2  639.06   725.6  643.43   757.4  646.91
#Mann= 7 ,-1 , 0
       0     .12       0   392.2    .045       0     408     .12       0
  430.58     .06       0  493.28     .12       0  497.89     .06       0
  541.94     .12       0
Bank Sta=392.2,408
XS Rating Curve= 0 ,0
Exp/Cntr=0.3,0.1

Type RM Length L Ch R = 1 ,839.6   ,164.2,164.4,162.9
XS GIS Cut Line= 2
     2372018.207      314499.301     2371656.228      313790.968
#Sta/Elev= 30
       0  618.54      24  619.86      48  620.13      60  621.21      76  619.06
    91.9  619.41   115.9  618.97   187.9  616.39   203.9  616.22   215.8  616.85
   223.8  616.12   295.8  615.64   355.8  613.02  377.95612.8538  404.21612.0305
   432.3     610   435.7  609.63   447.3  610.06   451.7  610.48  487.05609.5684
   503.7     609  552.72611.2392   583.6  611.73   623.6  615.51   642.1615.8513
  650.51616.3701   699.5  620.21   707.5  620.12   767.5  623.22   795.5  625.31
#Mann= 9 ,-1 , 0
       0     .12       0  377.95     .06       0  404.21     .12       0
   432.3    .045       0   447.3     .12       0  487.05     .06       0
  552.72     .12       0   642.1     .06       0  650.51     .12       0
Bank Sta=432.3,447.3
XS Rating Curve= 0 ,0
Exp/Cntr=0.3,0.1

Type RM Length L Ch R = 1 ,675.2   ,264,220.8,217.4
XS GIS Cut Line= 3
     2372353.276      314336.107     2372038.172      314198.086
     2371788.172      313716.315
#Sta/Elev= 30
       0  629.36    27.7  629.09    55.4  627.11      83  627.47   106.8  625.82
   138.4  625.55   233.3  621.72   280.7  618.19   308.4  617.94     340   616.2
     436 612.956   447.8  611.92  484.78611.7379   511.6  610.38   551.5  609.74
   559.5  608.31   563.5  607.19   567.5  606.86   575.5  607.99  629.27607.5509
  629.56607.5712   667.3  610.78  684.33611.6178   703.2  613.61   723.2  613.84
  737.98614.9872     775   617.1     799  619.24   854.8  621.53   886.8  622.11
#Mann= 9 ,-1 , 0
       0     .12       0     436     .06       0  484.78     .12       0
   559.5    .045       0   575.5     .12       0  629.27     .06       0
  629.56     .12       0  684.33     .06       0  737.98     .12       0
Bank Sta=559.5,575.5
XS Rating Curve= 0 ,0
Exp/Cntr=0.3,0.1

Type RM Length L Ch R = 1 ,454.4   ,353.9,299.1,305.4
XS GIS Cut Line= 2
     2372352.547      314311.818      2371931.54      313652.096
#Sta/Elev= 30
       0  629.25      16  627.96    39.9  627.41    51.9  626.38    79.9  625.91
    99.8  626.16   171.7  624.26   187.7  622.77   235.6  620.01   251.6  619.86
   271.5  617.75   311.4  615.76   331.4  613.45   355.4  611.39  366.34609.7502
  402.48606.0533   435.2  605.45   444.6  604.63   455.2  604.31   459.6  604.56
   499.1  606.25   515.1  606.42     559  610.53     571  610.58   658.8  614.78
  670.51614.8335   680.8  615.51   730.7  619.12   766.6  621.15   782.6  621.51
#Mann= 7 ,-1 , 0
       0     .12       0  366.34     .06       0  402.48     .12       0
   444.6    .045       0   459.6     .12       0  670.51     .06       0
   680.8     .12       0
Bank Sta=444.6,459.6
XS Rating Curve= 0 ,0
Exp/Cntr=0.3,0.1

Type RM Length L Ch R = 1 ,155.3   ,122.9,120.4,117.9
XS GIS Cut Line= 5
     2372388.138      314297.061     2372298.728      314145.151
     2372383.797      313882.998     2372268.346      313698.971
     2371996.645      313610.429
#Sta/Elev= 30
       0  629.83    50.9   627.5   156.7  624.45   232.2  619.99   272.1  613.73
   304.1  606.69     328  604.14     340   604.5     368  603.02   411.9  604.44
   427.9  603.68  480.86603.7866  508.08  603.19   515.1  603.32   526.9  602.79
     532   603.3   538.8  604.07   550.6  603.48   590.1  604.93   613.8   603.4
   653.3  607.77   669.1  606.72   700.9  606.86   764.4  608.46   800.1  609.98
   843.8   613.8  876.03615.2518  899.56617.0395     939  620.75   954.9  620.69
#Mann= 7 ,-1 , 0
       0     .12       0  480.86     .06       0  508.08     .12       0
   515.1    .045       0     532     .12       0  876.03     .06       0
  899.56     .12       0
#XS Ineff= 2 , 0
           461.3  604.92
Permanent Ineff=
       F       F
Bank Sta=515.1,532
XS Rating Curve= 0 ,0
Exp/Cntr=0.3,0.1

Type RM Length L Ch R = 1 ,34.9    ,45.6,34.9,24.2
XS GIS Cut Line= 4
     2372498.242      314264.926     2372545.117      313882.114
     2372279.492      313548.781      2372020.95      313511.123
#Sta/Elev= 30
       0  628.42    27.8  628.04    83.5   624.6   115.3  620.73   127.2  618.07
     167   613.4   186.9  609.86   218.7  607.38   230.6  607.73   254.5  605.83
   298.2  606.18   322.1  604.17   353.9  603.36   385.7  603.88   433.5  601.79
   501.2  600.62   513.1  599.31     549  601.48  573.75  600.43   580.9  599.57
  590.89  600.45   648.6  600.23   668.5   601.4   692.4  600.84   720.3  602.12
   819.8   602.8   875.2  606.47   883.2  608.16     899  608.08  1073.2  620.91
#Mann= 3 ,-1 , 0
       0     .12       0  573.75    .045       0  590.89     .12       0
#XS Ineff= 2 , 0
          505.26  602.09  611.76          601.98
Permanent Ineff=
       F       F
Bank Sta=573.75,590.89
XS Rating Curve= 0 ,0
Exp/Cntr=0.3,0.1

Chan Stop Cuts=-1
Use User Specified Reach Order=0
Composite Channel Slope=5